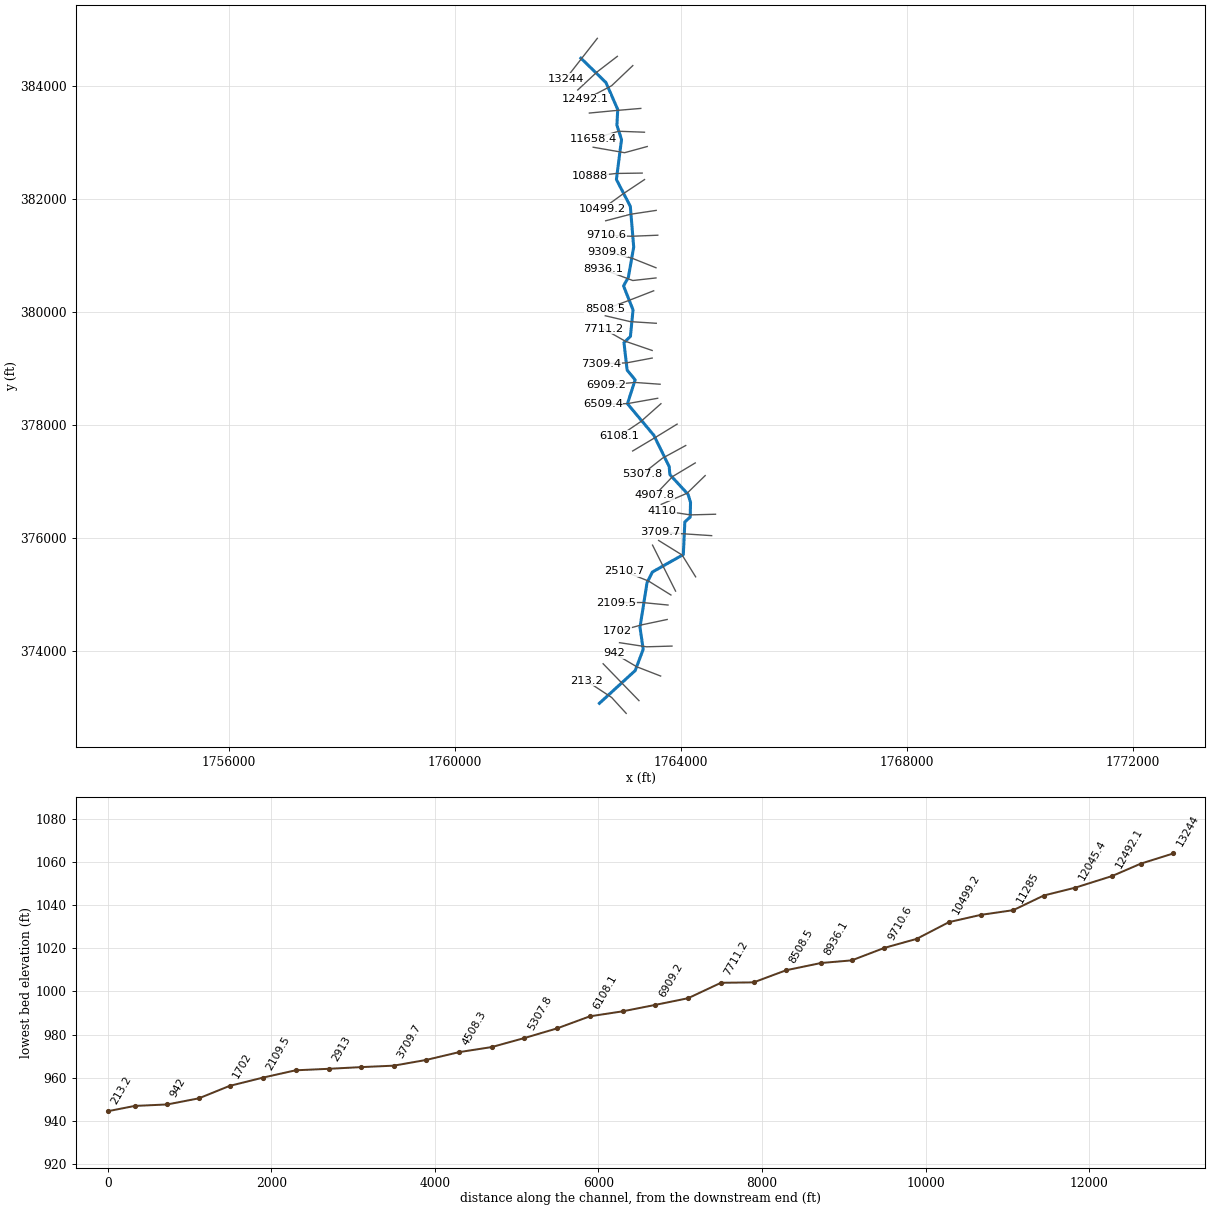
--- BthlRn.prj (project) ---

Proj Title=BthlRn
Current Plan=p01
Default Exp/Contr=0,0
English Units
Geom File=g01
Flow File=f01
Plan File=p01
BEGIN DESCRIPTION:
END DESCRIPTION:
DSS Export Rating Curves= 0
DSS Export Rating Curve Sorted= 0
DSS Export Volume Flow Curves= 0
DXF OffsetX= 0
DXF OffsetY= 0
DXF ScaleX= 0
DXF ScaleY= 0

--- BthlRn.p01 (plan) ---

Plan Title=Floodplain
Program Version=4.00
Geom File=g01
Flow File=f01
K Sum by GR=0
Std Step Tol=0.01
Critical Tol=0.01
Num of Std Step Trials=20
Max Error Tol=0.3
Flow Tol Ratio=0.001
Split Flow NTrial=30
Split Flow Tol=0.02
Split Flow Ratio=0.02
Log Output Level=0
Friction Slope Method=1
Unsteady Friction Slope Method=2
Unsteady Bridges Friction Slope Method=1
Global Log Level=0
CheckData=False
Run HTab=0
Run UNet=0
Run PostProcess=0
UNET Theta=0
UNET Theta Warmup=0
UNET ZTol=0
UNET ZSATol=0
UNET MxIter=0
UNET MaxInSteps=0
UNET DtIC=0
UNET DtMin=0
UNET MaxCRTS=0
UNET WFStab=0
UNET SFStab=0
UNET WFX=0
UNET SFX=0
UNET DSS MLevel=0
UNET DZMax Abort=0
UNET Convert EG Bridges=0
UNET Use Existing IB Tables=0
UNET Froude Limit=0
UNET Froude Power=0
Write IC File=0
Echo Input=False
Echo Output=False
Write Detailed=0

--- BthlRn.f01 (steady flow) ---

Flow Title=NFF Regression Equation
Program Version=4.00
Number of Profiles= 1
Profile Names=P100yr
River Rch & RM=BthlRn,Main            ,13244
743.2307
River Rch & RM=BthlRn,Main            ,12844.1
751.6076
River Rch & RM=BthlRn,Main            ,12045.4
979.1084
River Rch & RM=BthlRn,Main            ,11658.4
1076.806
River Rch & RM=BthlRn,Main            ,10888
1168.782
River Rch & RM=BthlRn,Main            ,8508.5
1339.363
River Rch & RM=BthlRn,Main            ,8110.2
1462.064
River Rch & RM=BthlRn,Main            ,4110
1782.753
River Rch & RM=BthlRn,Main            ,3709.7
1880.359
River Rch & RM=BthlRn,Main            ,213.2
 1882.59
Boundary for River Rch & Prof#=BthlRn,Main            , 1
Up Type= 0
Dn Type= 3
Dn Slope=0.006373
DSS Import GetInterval= 0
DSS Import GetPeak= 0
DSS Import FillOption= 0

--- BthlRn.g01 (geometry) ---

Geom Title=USGS 3m DEM
Program Version=4.00

River Reach=BthlRn     ,Main
Reach XY= 30
     1762228.325      384499.944     1762671.241      384068.633
     1762880.175      383590.576     1762865.314      383312.672
     1762947.051      383058.545     1762856.397      382351.151
     1763102.552      381877.265     1763162.509      381153.901
     1763067.737      380616.213     1762982.636      380467.286
     1763150.905      380041.777     1763104.486      379571.784
     1762990.372      379461.539     1763046.462      378976.072
     1763187.653      378802.000     1763052.264      378380.361
     1763520.323      377819.463     1763791.101      377266.302
     1763802.706      377125.111     1764123.772      376776.968
     1764168.257      376633.842     1764162.454      376372.735
     1764067.682      376287.633     1764040.604      375709.329
     1763493.245      375399.868     1763398.473      375212.257
     1763273.997      374421.207     1763330.470      374030.357
     1763189.587      373655.284     1762555.193      373075.045

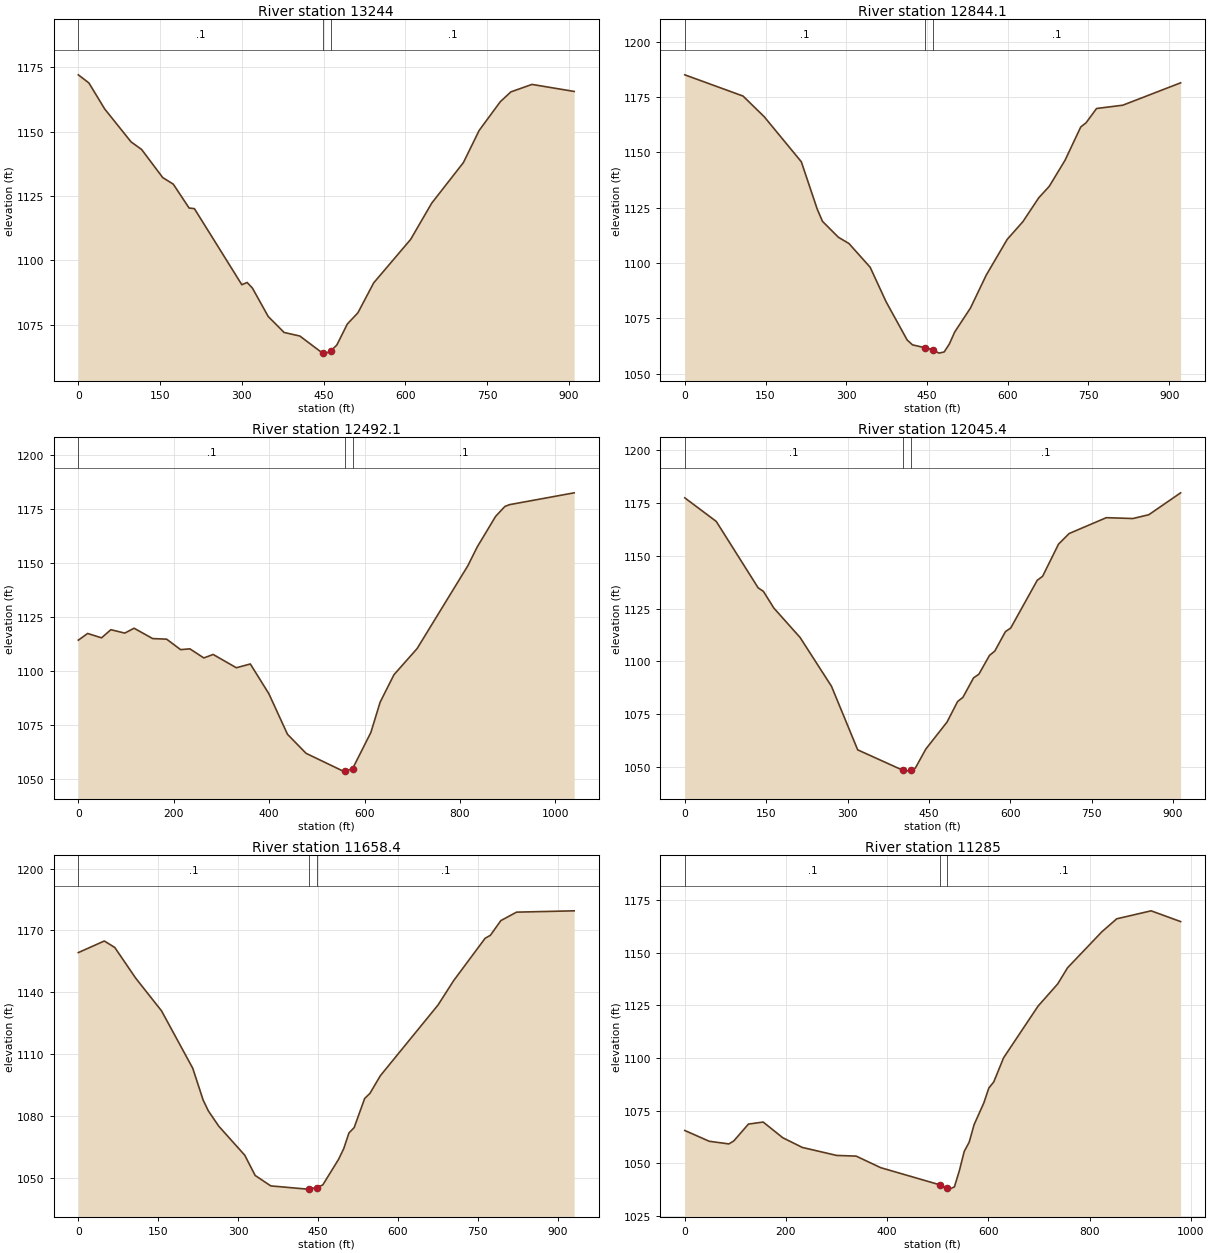
Type RM Length L Ch R = 1 ,13244,400.033,399.872,390.746
XS GIS Cut Line= 3
     1762519.128      384850.989     1762239.181      384492.305
     1761959.233      384133.621
#Sta/Elev= 30
       0 1172.03    19.4 1168.88    48.4 1158.78    96.8 1146.00   116.2 1143.05
   154.9 1132.15   174.3 1129.59   203.3 1120.33   213.0 1120.10   300.1 1090.56
   309.8 1091.43   319.5 1089.26   348.5 1078.24   377.6 1072.04   406.6 1070.64
   448.2 1064.02   455.0 1064.01   463.2 1064.85   474.4 1067.15   493.7 1075.31
   513.1 1079.66   542.1 1091.28   609.9 1108.15   648.6 1122.23   706.7 1137.96
   735.7 1150.46   774.5 1161.61   793.8 1165.40   832.6 1168.31   910.0 1165.58
#Mann= 3 , 0 , 0
       0     0.1       0   448.2   0.045       0   463.2     0.1       0
Bank Sta=   448.2,   463.2
Exp/Cntr=0.3,0.1

Type RM Length L Ch R = 1 ,12844.1,356.137,352.037,345.912
XS GIS Cut Line= 3
     1762873.380      384532.173     1762514.638      384256.220
     1762172.257      383936.270
#Sta/Elev= 30
       0 1185.13   108.2 1175.53   147.6 1166.17   216.5 1145.81   246.0 1124.42
   255.8 1118.86   285.3 1111.67   305.0 1108.83   344.4 1098.09   373.9 1082.53
   413.2 1065.17   423.1 1062.99   446.6 1061.67   461.6 1060.73   472.1 1059.25
   481.9 1059.78   491.6 1063.41   501.4 1068.79   530.7 1079.63   560.0 1094.51
   599.0 1110.70   628.3 1118.76   657.6 1129.51   677.1 1134.68   706.4 1146.46
   735.7 1161.57   745.5 1163.42   765.0 1169.90   813.8 1171.39   921.2 1181.51
#Mann= 3 , 0 , 0
       0     0.1       0   446.6   0.045       0   461.6     0.1       0
Bank Sta=   446.6,   461.6
Exp/Cntr=0.3,0.1

Type RM Length L Ch R = 1 ,12492.1,455.785,446.698,437.612
XS GIS Cut Line= 3
     1763146.622      384368.179     1762772.411      384012.223
     1762309.457      383768.887
#Sta/Elev= 30
       0 1114.27    19.5 1117.38    48.7 1115.35    68.2 1119.13    97.4 1117.55
   116.9 1119.81   155.9 1115.00   185.1 1114.74   214.4 1109.88   233.9 1110.24
   263.1 1106.02   282.6 1107.64   331.3 1101.47   360.6 1103.22   399.5 1089.40
   438.5 1070.59   477.5 1061.75   555.2 1053.49   560.1 1053.51   575.1 1054.68
   613.3 1071.44   632.7 1085.48   661.7 1098.23   710.2 1110.36   816.7 1148.84
   836.1 1157.46   874.8 1171.71   894.2 1176.31   903.9 1177.16  1039.5 1182.65
#Mann= 3 , 0 , 0
       0     0.1       0   560.1   0.045       0   575.1     0.1       0
Bank Sta=   560.1,   575.1
Exp/Cntr=0.3,0.1

Type RM Length L Ch R = 1 ,12045.4,389.77,386.988,385.691
XS GIS Cut Line= 3
     1763288.263      383610.027     1762835.790      383571.681
     1762377.753      383527.854
#Sta/Elev= 30
       0 1177.34    58.0 1166.21   135.3 1134.79   144.9 1133.15   164.2 1125.24
   212.6 1111.33   270.5 1088.25   318.8 1058.21   402.4 1048.52   405.8 1048.15
   417.4 1048.49   425.1 1049.59   444.4 1058.59   483.5 1071.34   503.0 1081.06
   512.8 1083.03   532.4 1092.24   542.2 1093.96   561.8 1102.86   571.6 1104.91
   591.2 1114.11   600.9 1115.79   649.9 1138.39   659.7 1140.25   689.1 1155.47
   708.6 1160.47   777.2 1167.97   826.1 1167.57   855.5 1169.36   914.2 1179.72
#Mann= 3 , 0 , 0
       0     0.1       0   402.4   0.045       0   417.4     0.1       0
Bank Sta=   402.4,   417.4
Exp/Cntr=0.3,0.1

Type RM Length L Ch R = 1 ,11658.4,376.554,373.429,368.819
XS GIS Cut Line= 3
     1763353.178      383188.615     1762894.449      383205.408
     1762441.894      383070.987
#Sta/Elev= 30
       0 1159.25    48.8 1164.87    68.4 1161.75   107.4 1146.96   156.3 1130.95
   214.9 1103.12   234.4 1087.69   244.2 1082.44   263.7 1075.03   312.5 1060.96
   332.1 1051.12   361.4 1046.06   429.7 1044.49   432.7 1044.53   447.7 1045.22
   459.0 1046.52   488.5 1058.86   498.4 1064.13   508.2 1071.74   518.0 1074.36
   537.7 1088.46   547.6 1090.96   567.2 1099.53   675.4 1133.79   704.9 1145.68
   763.9 1166.19   773.8 1167.64   793.4 1174.76   822.9 1178.87   931.1 1179.51
#Mann= 3 , 0 , 0
       0     0.1       0   432.7   0.045       0   447.7     0.1       0
Bank Sta=   432.7,   447.7
Exp/Cntr=0.3,0.1

Type RM Length L Ch R = 1 ,11285,393.538,397.006,402.563
XS GIS Cut Line= 3
     1763402.180      382935.228     1763000.588      382825.703
     1762445.232      382922.772
#Sta/Elev= 30
       0 1065.54    48.4 1060.42    87.1 1059.17    96.8 1060.57   125.8 1068.59
   154.9 1069.55   193.6 1062.11   232.3 1057.49   300.1 1053.70   338.8 1053.37
   387.2 1047.88     504 1039.74     519 1038.01   523.2 1037.69   532.9 1038.77
   542.6 1046.38   552.3 1055.61   562.1 1060.01   571.8 1068.32   591.2 1078.73
   600.9 1085.70   610.7 1088.63   630.1 1100.08   698.1 1124.59   737.0 1135.15
   756.5 1142.84   824.5 1159.97   853.7 1166.10   921.7 1169.89   980.0 1164.78
#Mann= 3 , 0 , 0
       0     0.1       0     504   0.045       0     519     0.1       0
Bank Sta=     504,     519
Exp/Cntr=0.3,0.1

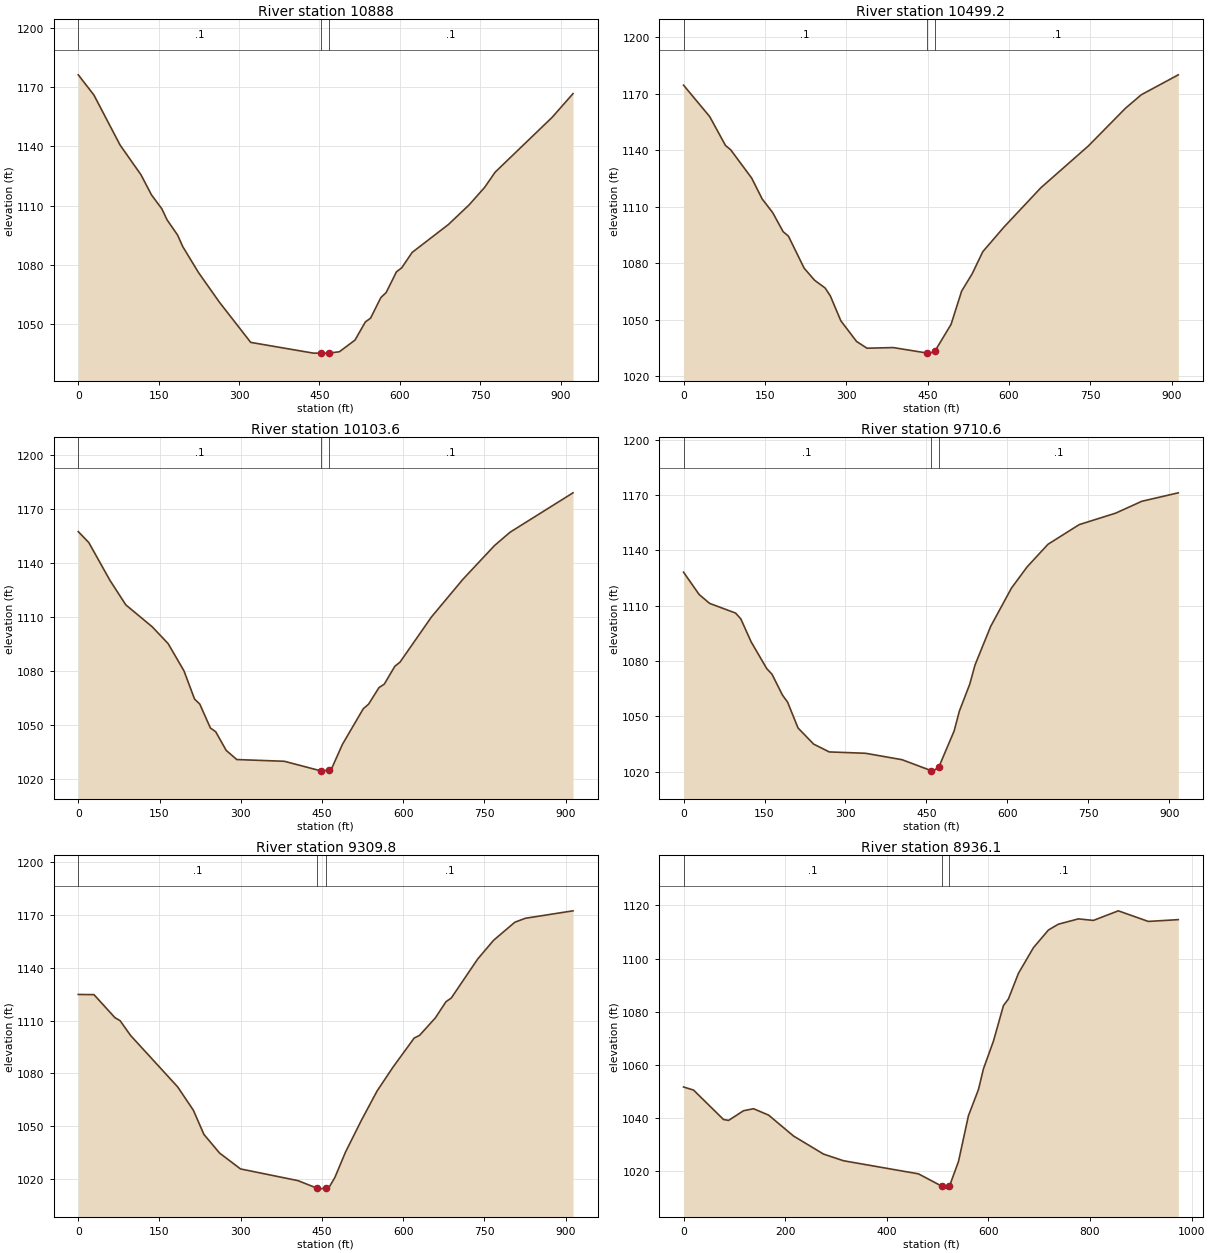
Type RM Length L Ch R = 1 ,10888,375.886,388.765,400.378
XS GIS Cut Line= 3
     1763313.045      382464.796     1762854.980      382458.105
     1762393.135      382405.142
#Sta/Elev= 30
       0 1176.13    29.2 1165.91    78.0 1140.65   117.0 1125.63   136.5 1115.51
   156.0 1108.38   165.7 1102.84   185.2 1095.21   194.9 1089.35   224.2 1076.27
   263.2 1061.29   321.7 1040.94   438.6 1035.51   452.2 1035.51   467.2 1035.51
   487.2 1036.21   516.2 1042.09   535.6 1051.27   545.3 1053.18   564.6 1063.61
   574.3 1066.09   593.7 1076.62   603.4 1078.60   622.8 1086.38   690.5 1100.49
   729.3 1110.45   758.3 1119.32   777.7 1126.94   884.2 1154.69   923.0 1166.63
#Mann= 3 , 0 , 0
       0     0.1       0   452.2   0.045       0   467.2     0.1       0
Bank Sta=   452.2,   467.2
Exp/Cntr=0.3,0.1

Type RM Length L Ch R = 1 ,10499.2,405.776,395.642,386.751
XS GIS Cut Line= 3
     1763354.211      382350.079     1762976.080      382097.990
     1762605.263      381829.054
#Sta/Elev= 30
       0 1174.49    48.3 1157.77    77.4 1142.44    87.0 1140.15   125.7 1125.11
   145.0 1114.05   164.4 1106.80   183.7 1096.66   193.4 1094.32   222.4 1077.29
   241.7 1070.86   261.1 1066.75   270.7 1062.57   290.1 1049.34   319.1 1038.36
   338.4 1034.76   386.8 1035.10   448.6 1032.22   454.5 1032.15   463.6 1033.20
   493.4 1047.41   512.9 1065.08   532.4 1074.31   551.9 1086.02   590.9 1099.07
   659.1 1120.00   746.8 1142.23   815.1 1162.22   844.3 1169.39   912.5 1179.97
#Mann= 3 , 0 , 0
       0     0.1       0   448.6   0.045       0   463.6     0.1       0
Bank Sta=   448.6,   463.6
Exp/Cntr=0.3,0.1

Type RM Length L Ch R = 1 ,10103.6,395.674,392.992,386.813
XS GIS Cut Line= 3
     1763560.509      381803.970     1763106.954      381735.859
     1762666.900      381620.208
#Sta/Elev= 30
       0 1157.46    19.5 1151.35    58.5 1130.37    87.8 1116.75   136.6 1104.56
   165.9 1095.24   195.2 1080.08   214.7 1064.43   224.4 1061.62   244.0 1048.34
   253.7 1046.29   273.2 1035.88   292.7 1030.81   380.6 1029.84   447.6 1024.54
   448.9 1024.37   462.6 1025.08   468.3 1026.07   487.7 1039.19   526.4 1059.09
   536.1 1061.57   555.4 1070.82   565.1 1072.71   584.5 1082.61   594.2 1084.96
   652.3 1110.07   710.3 1130.97   768.4 1149.64   797.5 1157.15   913.6 1179.01
#Mann= 3 , 0 , 0
       0     0.1       0   447.6   0.045       0   462.6     0.1       0
Bank Sta=   447.6,   462.6
Exp/Cntr=0.3,0.1

Type RM Length L Ch R = 1 ,9710.6,410.021,400.723,395.035
XS GIS Cut Line= 3
     1763588.921      381364.577     1763126.554      381345.779
     1762672.925      381360.572
#Sta/Elev= 30
       0 1128.13    28.9 1116.04    48.2 1111.22    96.4 1105.96   106.0 1102.87
   125.3 1090.31   154.2 1075.82   163.9 1072.79   183.2 1061.52   192.8 1057.64
   212.1 1043.64   241.0 1034.88   269.9 1030.64   337.4 1029.90   404.9 1026.42
   458.3 1020.53   462.7 1020.22   473.3 1022.65   501.4 1042.06   511.0 1052.73
   530.3 1067.43   540.0 1077.77   569.0 1098.72   607.6 1119.54   636.6 1131.03
   675.2 1143.27   733.1 1153.94   800.7 1160.17   849.0 1166.59   916.6 1171.18
#Mann= 3 , 0 , 0
       0     0.1       0   458.3   0.045       0   473.3     0.1       0
Bank Sta=   458.3,   473.3
Exp/Cntr=0.3,0.1

Type RM Length L Ch R = 1 ,9309.8,372.948,373.766,372.406
XS GIS Cut Line= 3
     1763556.962      380788.141     1763135.060      380956.505
     1762691.064      381074.633
#Sta/Elev= 30
       0 1124.77    29.0 1124.67    67.7 1111.62    77.3 1109.88    96.6 1101.53
   183.6 1072.35   212.6 1059.11   232.0 1045.45   261.0 1034.85   299.6 1025.87
   405.9 1019.21   441.8 1014.84   444.6 1014.41   456.8 1015.12   464.0 1015.87
   473.8 1020.96   493.4 1035.32   522.7 1053.31   552.0 1070.13   581.3 1083.59
   620.4 1100.06   630.2 1101.55   659.5 1111.49   679.1 1120.66   688.9 1122.76
   737.7 1144.88   767.1 1155.50   806.2 1165.71   825.7 1167.96   913.7 1172.18
#Mann= 3 , 0 , 0
       0     0.1       0   441.8   0.045       0   456.8     0.1       0
Bank Sta=   441.8,   456.8
Exp/Cntr=0.3,0.1

Type RM Length L Ch R = 1 ,8936.1,411.245,427.603,443.575
XS GIS Cut Line= 3
     1763557.340      380607.823     1763146.622      380562.188
     1762621.785      380758.863
#Sta/Elev= 30
       0 1051.65    19.7 1050.48    78.7 1039.41    88.6 1039.06   118.1 1042.71
   137.7 1043.46   167.3 1041.08   216.5 1033.19   275.5 1026.39   314.9 1023.88
   462.4 1018.95   508.3 1014.31   521.4 1013.20   523.3 1014.28   541.1 1023.58
   560.7 1040.83   580.4 1050.67   590.2 1058.45   609.9 1068.89   629.6 1082.28
   639.4 1084.79   659.1 1094.42   688.6 1104.07   718.1 1110.72   737.7 1112.92
   777.1 1114.92   806.6 1114.34   855.7 1117.95   914.7 1113.96   973.7 1114.63
#Mann= 3 , 0 , 0
       0     0.1       0   508.3   0.045       0   523.3     0.1       0
Bank Sta=   508.3,   523.3
Exp/Cntr=0.3,0.1

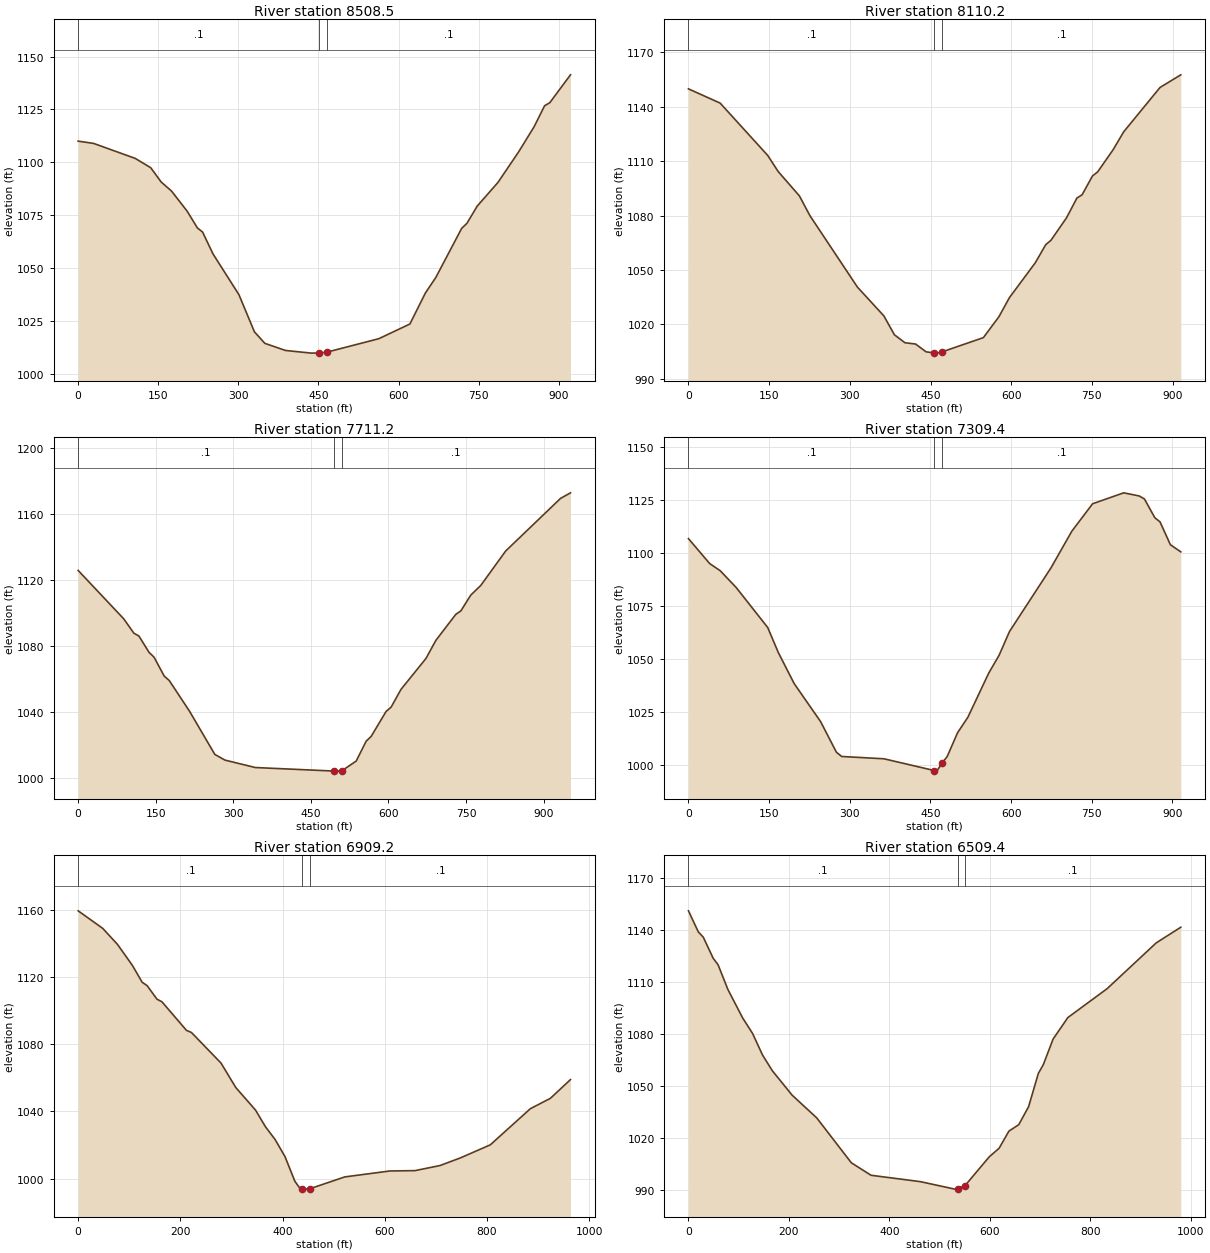
Type RM Length L Ch R = 1 ,8508.5,408.673,398.247,384.942
XS GIS Cut Line= 3
     1763515.962      380380.192     1763090.784      380214.363
     1762654.267      380052.665
#Sta/Elev= 30
       0 1110.03    29.1 1108.94   106.8 1101.87   135.9 1097.47   155.4 1090.73
   174.8 1086.44   203.9 1077.00   223.3 1069.01   233.0 1067.06   252.5 1056.73
   301.0 1037.49   330.1 1019.90   349.6 1014.46   388.4 1011.09   437.0 1009.84
   450.5 1009.92   465.5 1010.29   563.0 1016.66   621.2 1023.60   650.3 1038.29
   669.7 1045.58   718.2 1068.82   727.9 1071.15   747.3 1079.34   786.1 1090.51
   824.9 1104.98   854.0 1116.92   873.4 1126.74   883.1 1128.17   921.9 1141.36
#Mann= 3 , 0 , 0
       0     0.1       0   450.5   0.045       0   465.5     0.1       0
Bank Sta=   450.5,   465.5
Exp/Cntr=0.3,0.1

Type RM Length L Ch R = 1 ,8110.2,405.616,399.052,391.707
XS GIS Cut Line= 3
     1763562.001      379804.966     1763101.497      379834.117
     1762659.696      379938.068
#Sta/Elev= 30
       0 1149.90    58.9 1142.05   147.3 1113.22   166.9 1104.28   206.2 1090.92
   225.8 1080.00   314.2 1040.58   363.2 1024.77   382.9 1014.32   402.5 1009.93
   422.2 1009.23   441.8 1004.93   457.2 1004.29   461.4 1004.21   472.2 1004.97
   548.3 1012.76   577.3 1024.33   596.6 1034.76   644.9 1054.08   664.2 1064.00
   673.9 1066.41   702.8 1078.79   722.2 1089.72   731.8 1091.51   751.1 1101.88
   760.8 1104.14   789.8 1116.50   809.1 1126.21   876.7 1150.67   915.3 1157.64
#Mann= 3 , 0 , 0
       0     0.1       0   457.2   0.045       0   472.2     0.1       0
Bank Sta=   457.2,   472.2
Exp/Cntr=0.3,0.1

Type RM Length L Ch R = 1 ,7711.2,389.601,401.766,414.922
XS GIS Cut Line= 3
     1763489.017      379323.519     1763016.928      379485.687
     1762623.205      379709.568
#Sta/Elev= 30
       0 1125.59    88.1 1096.29   107.7 1087.59   117.5 1085.86   137.0 1076.01
   146.8 1073.04   166.4 1061.59   176.2 1058.90   215.3 1040.36   264.3 1014.15
   283.8 1010.71   342.6 1006.20   494.9 1004.05   499.2 1004.02   509.9 1004.21
   537.7 1010.12   557.0 1022.18   566.6 1025.03   595.5 1040.17   605.2 1042.77
   624.4 1053.57   672.6 1072.26   691.9 1083.28   730.4 1099.01   740.1 1101.07
   759.4 1110.69   778.6 1116.49   826.8 1137.37   932.8 1169.20   952.1 1172.60
#Mann= 3 , 0 , 0
       0     0.1       0   494.9   0.045       0   509.9     0.1       0
Bank Sta=   494.9,   509.9
Exp/Cntr=0.3,0.1

Type RM Length L Ch R = 1 ,7309.4,405.768,400.181,400.737
XS GIS Cut Line= 3
     1763489.859      379189.024     1763035.914      379103.598
     1762582.386      379088.481
#Sta/Elev= 30
       0 1106.86    39.3 1095.10    59.0 1091.69    88.5 1083.82   147.4 1064.81
   167.1 1052.98   196.6 1038.29   245.7 1020.33   275.2 1005.80   285.0 1003.80
   363.6 1002.71   457.3  997.14   461.9  996.87   472.3 1000.89   481.2 1003.78
   500.5 1015.03   519.8 1022.41   558.5 1043.26   577.8 1051.71   597.1 1062.92
   674.3 1093.05   712.9 1110.33   751.6 1123.35   809.5 1128.53   838.5 1127.04
   848.1 1125.61   867.4 1116.75   877.1 1114.78   896.4 1103.96   915.7 1100.60
#Mann= 3 , 0 , 0
       0     0.1       0   457.3   0.045       0   472.3     0.1       0
Bank Sta=   457.3,   472.3
Exp/Cntr=0.3,0.1

Type RM Length L Ch R = 1 ,6909.2,395.116,399.818,398.59
XS GIS Cut Line= 3
     1763629.885      378725.422     1763187.519      378757.019
     1762669.346      378711.075
#Sta/Elev= 30
       0 1159.31    48.2 1148.85    77.1 1139.31   106.1 1126.89   125.3 1116.82
   135.0 1114.81   154.3 1106.76   163.9 1105.24   212.1 1088.18   221.7 1086.96
   279.6 1068.77   308.5 1054.23   347.1 1040.84   366.4 1030.99   385.6 1023.25
   404.9 1013.11   424.2  998.46   433.9  994.32   439.1  994.03   443.5  993.77
   454.1  994.06   522.0 1001.04   610.4 1004.57   659.4 1004.77   708.5 1007.82
   747.8 1012.29   806.7 1020.10   885.2 1041.62   924.4 1047.78   963.7 1058.93
#Mann= 3 , 0 , 0
       0     0.1       0   439.1   0.045       0   454.1     0.1       0
Bank Sta=   439.1,   454.1
Exp/Cntr=0.3,0.1

Type RM Length L Ch R = 1 ,6509.4,388.157,401.313,414.516
XS GIS Cut Line= 3
     1763587.167      378476.803     1763055.237      378382.875
     1762615.679      378368.486
#Sta/Elev= 30
       0 1151.03    19.6 1138.90    29.5 1135.85    49.1 1123.78    58.9 1119.98
    78.6 1105.69   108.0 1089.28   127.7 1080.38   147.3 1068.07   167.0 1058.94
   206.2 1044.93   255.3 1031.82   324.1 1005.98   363.4  998.77   461.6  995.10
   530.3  990.79   535.6  991.09   550.6  992.85   598.8 1009.42   618.3 1014.30
   637.9 1024.21   657.4 1027.88   677.0 1038.22   696.5 1057.46   706.3 1062.43
   725.8 1077.19   755.2 1089.58   833.4 1106.22   931.1 1132.58   980.0 1141.58
#Mann= 3 , 0 , 0
       0     0.1       0   535.6   0.045       0   550.6     0.1       0
Bank Sta=   535.6,   550.6
Exp/Cntr=0.3,0.1

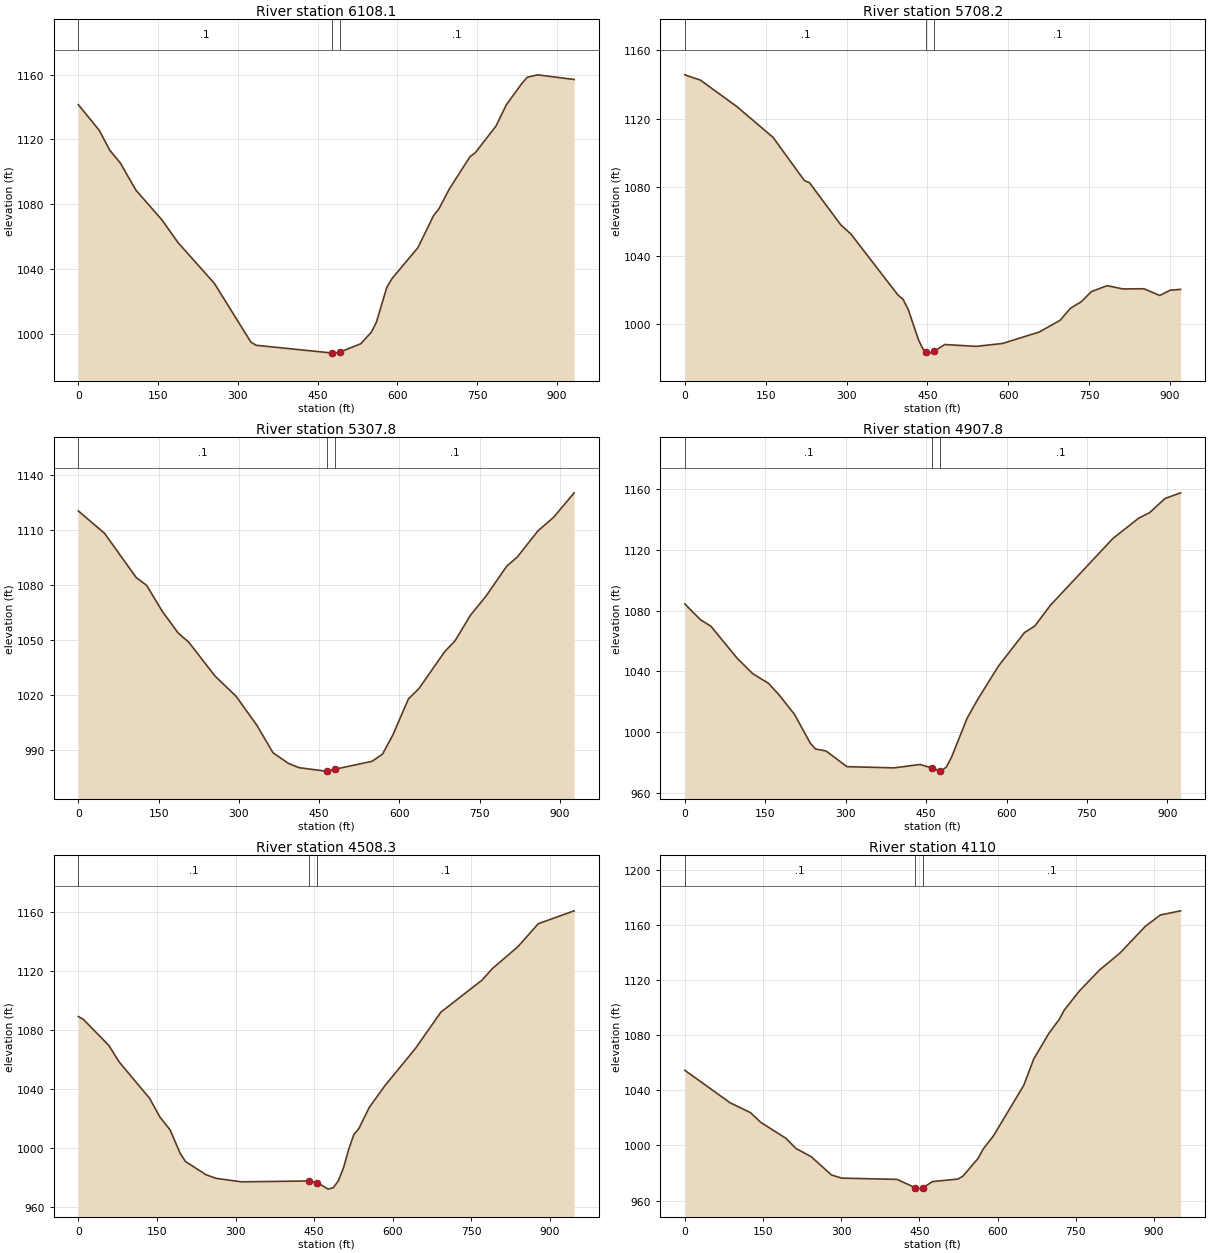
Type RM Length L Ch R = 1 ,6108.1,403.403,399.903,398.914
XS GIS Cut Line= 3
     1763644.531      378380.699     1763283.927      378060.656
     1762911.025      377808.399
#Sta/Elev= 30
       0 1141.43    39.4 1125.63    59.0 1113.44    78.7 1105.64   108.2 1088.87
   157.4 1070.42   187.0 1056.73   255.8 1031.43   324.7  995.17   334.5  993.30
   476.3  988.57   482.1  988.47   491.3  989.02   531.1  994.26   550.7 1001.22
   560.4 1007.38   580.0 1028.91   589.8 1034.36   638.7 1053.46   668.1 1073.18
   677.9 1077.20   697.5 1089.44   736.6 1109.45   746.4 1111.79   785.5 1128.32
   805.1 1141.49   834.5 1154.68   844.3 1158.30   863.8 1159.81   932.4 1156.93
#Mann= 3 , 0 , 0
       0     0.1       0   476.3   0.045       0   491.3     0.1       0
Bank Sta=   476.3,   491.3
Exp/Cntr=0.3,0.1

Type RM Length L Ch R = 1 ,5708.2,401.801,400.347,403.481
XS GIS Cut Line= 3
     1763931.151      378019.291     1763544.976      377782.603
     1763144.253      377543.394
#Sta/Elev= 30
       0 1145.74    28.9 1142.66    96.4 1127.20   163.8 1109.12   221.6 1083.95
   231.3 1082.60   289.1 1058.03   308.4 1052.48   395.1 1016.97   404.8 1014.38
   414.4 1008.44   433.7  990.45   443.3  984.39   447.2  983.78   452.9  982.89
   462.2  983.89   482.1  987.93   540.4  986.84   589.1  988.53   657.1  995.20
   696.0 1002.08   715.5 1009.21   734.9 1012.87   754.3 1018.92   783.5 1022.38
   812.7 1020.45   851.6 1020.57   880.7 1016.62   900.2 1019.70   919.6 1020.19
#Mann= 3 , 0 , 0
       0     0.1       0   447.2   0.045       0   462.2     0.1       0
Bank Sta=   447.2,   462.2
Exp/Cntr=0.3,0.1

Type RM Length L Ch R = 1 ,5307.8,398.123,400.057,404.018
XS GIS Cut Line= 3
     1764083.294      377640.337     1763669.281      377414.144
     1763312.462      377131.763
#Sta/Elev= 30
       0 1120.38    49.1 1108.12   108.1 1084.06   127.8 1079.72   157.3 1065.42
   186.7 1053.74   206.4 1048.77   255.5 1030.27   294.9 1019.24   334.2 1003.24
   363.7  988.48   393.1  982.54   412.8  980.28   461.9  978.40   464.8  978.48
   479.8  979.45   549.2  983.78   568.6  987.67   588.0  998.19   617.0 1017.79
   636.4 1023.34   684.8 1043.60   704.1 1049.48   733.2 1063.57   762.2 1073.94
   800.9 1090.29   820.3 1095.16   859.0 1109.45   888.1 1116.81   926.8 1130.25
#Mann= 3 , 0 , 0
       0     0.1       0   464.8   0.045       0   479.8     0.1       0
Bank Sta=   464.8,   479.8
Exp/Cntr=0.3,0.1

Type RM Length L Ch R = 1 ,4907.8,394.555,399.518,389.869
XS GIS Cut Line= 3
     1764251.844      377331.849     1763850.517      377090.655
     1763535.848      376759.917
#Sta/Elev= 30
       0 1084.47    29.3 1074.05    48.8 1069.73    97.5 1048.72   126.8 1038.44
   156.1 1032.11   175.6 1024.60   204.9 1011.48   234.1  992.61   243.9  988.80
   263.4  987.50   302.4  977.16   390.2  976.36   439.0  978.60   461.3  976.17
   476.3  974.31   477.9  974.21   487.7  976.87   497.4  983.34   526.5 1009.08
   545.9 1021.29   584.8 1043.41   633.4 1065.53   652.8 1069.92   681.9 1083.62
   798.5 1127.66   847.0 1141.16   866.5 1144.57   895.6 1154.00   924.7 1157.74
#Mann= 3 , 0 , 0
       0     0.1       0   461.3   0.045       0   476.3     0.1       0
Bank Sta=   461.3,   476.3
Exp/Cntr=0.3,0.1

Type RM Length L Ch R = 1 ,4508.3,415.987,398.318,385.392
XS GIS Cut Line= 3
     1764427.573      377107.656     1764107.579      376795.103
     1763649.586      376598.064
#Sta/Elev= 30
       0 1089.20     9.7 1087.23    58.3 1069.49    77.8 1058.37   136.1 1033.52
   155.6 1020.89   175.0 1012.18   194.5  996.05   204.2  990.72   243.1  981.73
   262.6  979.19   311.2  976.82     441  977.41     456  976.23   476.6  971.86
   486.4  972.82   496.2  977.63   506.0  986.46   515.7  998.83   525.5 1008.86
   535.3 1013.10   554.8 1027.26   584.2 1041.89   642.8 1067.36   691.7 1092.19
   769.9 1113.86   789.5 1121.66   838.4 1136.61   877.5 1152.30   945.9 1161.05
#Mann= 3 , 0 , 0
       0     0.1       0     441   0.045       0     456     0.1       0
Bank Sta=     441,     456
Exp/Cntr=0.3,0.1

Type RM Length L Ch R = 1 ,4110,398.595,400.269,404.139
XS GIS Cut Line= 3
     1764610.361      376423.349     1764164.364      376411.613
     1763664.938      376487.383
#Sta/Elev= 30
       0 1054.60    87.3 1030.90   126.1 1023.82   145.5 1016.86   194.0 1005.17
   213.4  997.75   242.5  991.83   281.3  978.59   300.7  976.28   407.4  975.33
   441.6  969.42   446.2  968.27   456.6  969.20   475.3  973.74   523.9  975.58
   533.6  977.67   562.7  990.61   572.4  997.33   591.9 1006.78   650.2 1043.55
   669.6 1062.89   698.7 1081.51   718.2 1091.42   727.9 1098.19   757.0 1112.16
   795.9 1127.46   834.7 1139.63   883.3 1159.03   912.4 1167.34   951.3 1170.38
#Mann= 3 , 0 , 0
       0     0.1       0   441.6   0.045       0   456.6     0.1       0
Bank Sta=   441.6,   456.6
Exp/Cntr=0.3,0.1

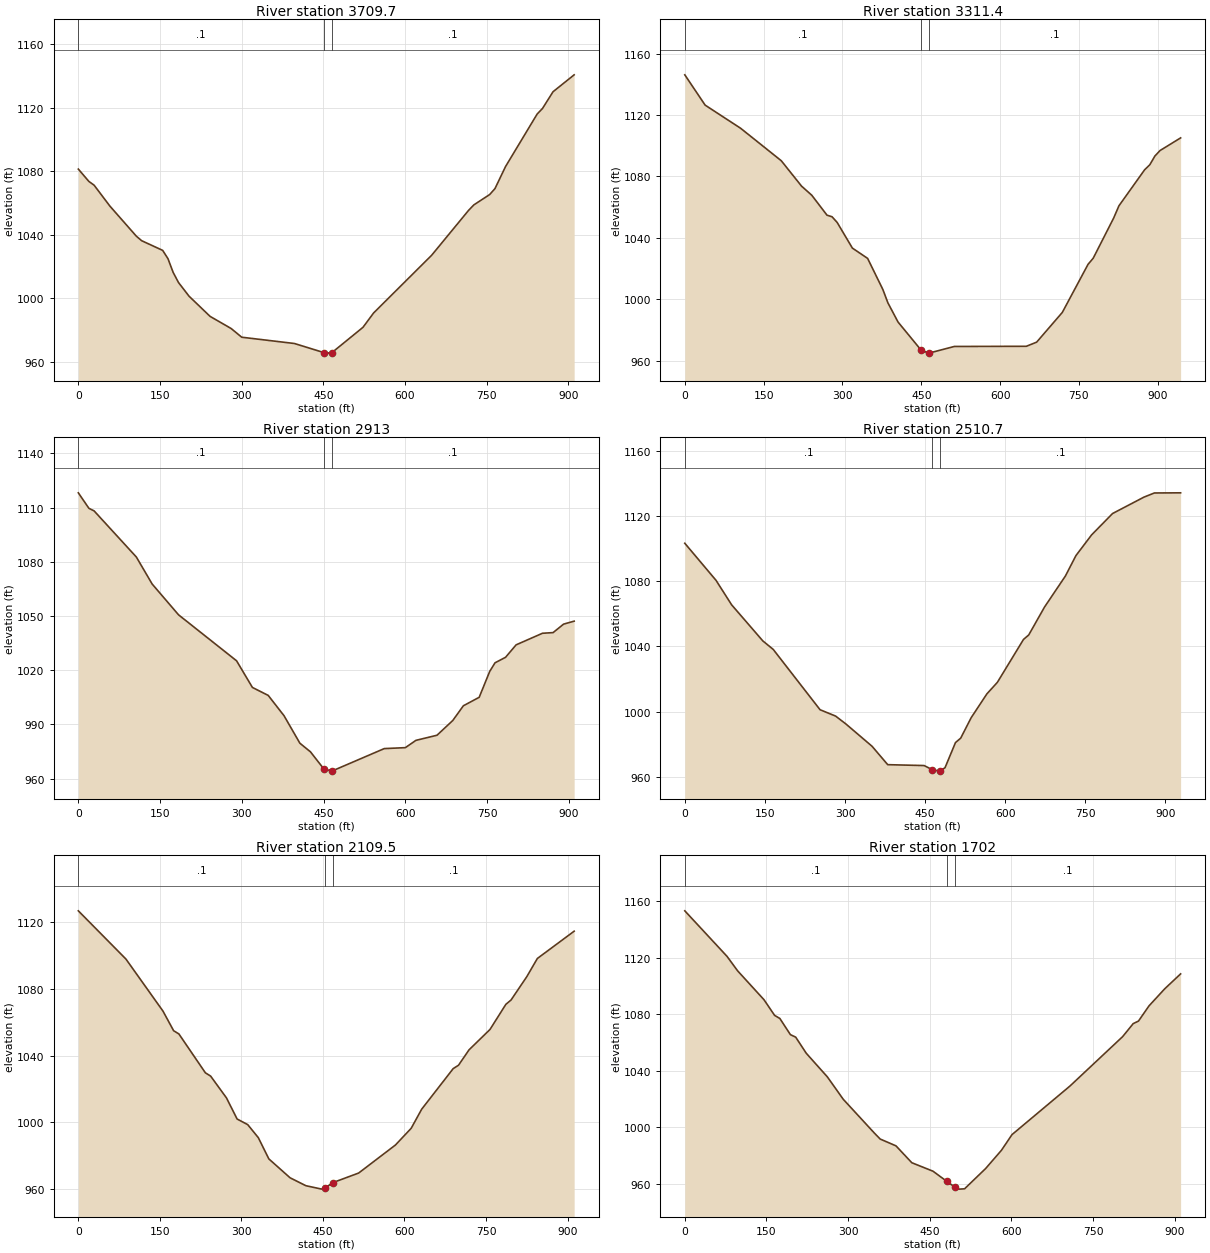
Type RM Length L Ch R = 1 ,3709.7,419.508,398.281,389.251
XS GIS Cut Line= 3
     1764542.104      376044.104     1764088.106      376073.930
     1763633.299      376100.749
#Sta/Elev= 30
       0 1081.40    19.4 1073.64    29.0 1071.27    58.1 1058.07   106.5 1039.20
   116.2 1036.36   154.9 1030.25   164.6 1025.05   174.2 1016.36   183.9 1010.06
   203.3 1001.43   242.0  988.71   280.7  981.07   300.1  975.60   396.9  971.65
   450.6  965.96   455.0  965.59   465.6  965.88   522.8  981.84   542.2  990.83
   648.8 1027.15   716.7 1055.43   726.4 1058.88   755.5 1065.40   765.2 1069.14
   784.6 1083.01   842.7 1116.08   852.4 1119.52   871.8 1130.08   910.6 1140.73
#Mann= 3 , 0 , 0
       0     0.1       0   450.6   0.045       0   465.6     0.1       0
Bank Sta=   450.6,   465.6
Exp/Cntr=0.3,0.1

Type RM Length L Ch R = 1 ,3311.4,401.718,398.417,382.442
XS GIS Cut Line= 3
     1764258.526      375314.760     1764019.620      375700.998
     1763603.731      375958.924
#Sta/Elev= 30
       0 1146.12    38.7 1126.39   106.3 1111.31   183.6 1090.18   222.2 1073.64
   241.6 1067.74   270.6 1054.73   280.2 1053.71   289.9 1050.03   318.9 1033.31
   347.9 1026.60   376.9 1006.35   386.5  997.65   405.8  985.15   449.7  966.87
   463.9  964.92   464.7  964.94   512.9  969.26   649.9  969.37   669.5  972.05
   718.4  991.44   767.4 1022.76   777.1 1026.67   816.3 1053.02   826.1 1060.83
   875.0 1084.29   884.8 1087.54   894.6 1093.27   904.4 1096.83   943.5 1105.06
#Mann= 3 , 0 , 0
       0     0.1       0   449.7   0.045       0   464.7     0.1       0
Bank Sta=   449.7,   464.7
Exp/Cntr=0.3,0.1

Type RM Length L Ch R = 1 ,2913,388.812,402.282,419.311
XS GIS Cut Line= 3
     1763903.413      375062.328     1763699.623      375469.138
     1763495.969      375876.017
#Sta/Elev= 30
       0 1118.13    19.4 1109.56    29.0 1108.12   106.5 1082.60   135.5 1067.67
   183.9 1050.63   290.4 1025.19   319.5 1010.44   348.5 1006.03   377.6  994.76
   406.6  979.58   426.0  974.82   450.2  965.50   464.7  964.13   465.2  964.13
   561.5  976.60   600.2  977.12   619.6  981.16   658.3  983.99   687.3  992.17
   706.7 1000.30   735.7 1004.98   755.1 1019.36   764.8 1024.08   784.1 1027.12
   803.5 1034.01   851.9 1040.42   871.3 1040.78   890.6 1045.47   910.0 1047.12
#Mann= 3 , 0 , 0
       0     0.1       0   450.2   0.045       0   465.2     0.1       0
Bank Sta=   450.2,   465.2
Exp/Cntr=0.3,0.1

Type RM Length L Ch R = 1 ,2510.7,391.013,401.196,409.739
XS GIS Cut Line= 3
     1763821.831      374993.096     1763424.769      375240.179
     1762996.852      375411.123
#Sta/Elev= 30
       0 1103.17    58.5 1080.43    87.7 1065.42   146.1 1043.30   165.6 1038.08
   253.3 1001.09   282.5  997.18   302.0  992.27   350.7  978.67   380.0  967.40
   448.2  966.86   463.6  964.30   477.5  963.44   478.6  963.67   487.3  965.52
   506.9  980.95   516.7  983.68   536.3  996.21   565.7 1010.81   585.3 1017.87
   634.3 1044.20   644.1 1046.95   673.6 1064.04   712.8 1083.12   732.4 1095.58
   761.8 1108.30   801.0 1121.39   859.8 1131.46   879.4 1134.01   928.5 1134.10
#Mann= 3 , 0 , 0
       0     0.1       0   463.6   0.045       0   478.6     0.1       0
Bank Sta=   463.6,   478.6
Exp/Cntr=0.3,0.1

Type RM Length L Ch R = 1 ,2109.5,399.319,407.497,413.763
XS GIS Cut Line= 3
     1763769.873      374815.312     1763314.410      374859.892
     1762859.876      374859.892
#Sta/Elev= 30
       0 1126.58    87.6 1097.71   155.8 1066.54   175.3 1054.84   185.0 1052.91
   233.7 1029.66   243.4 1027.68   272.6 1014.61   292.1 1002.00   311.6  998.65
   331.1  990.86   350.5  978.13   389.5  966.84   418.7  962.08   447.9  960.04
   453.1  960.53   468.1  963.91   515.7  969.66   583.4  986.44   612.4  996.45
   631.7 1007.88   689.7 1032.17   699.4 1034.16   718.8 1043.38   757.4 1055.60
   786.5 1070.60   796.1 1073.21   825.1 1087.19   844.5 1098.06   912.2 1114.39
#Mann= 3 , 0 , 0
       0     0.1       0   453.1   0.045       0   468.1     0.1       0
Bank Sta=   453.1,   468.1
Exp/Cntr=0.3,0.1

Type RM Length L Ch R = 1 ,1702,384.763,374.927,365.09
XS GIS Cut Line= 3
     1763755.305      374559.435     1763309.307      374465.220
     1762870.132      374346.833
#Sta/Elev= 30
       0 1153.09    77.6 1120.86    97.0 1110.65   145.5 1090.18   164.9 1079.14
   174.6 1076.93   194.0 1065.48   203.7 1063.71   223.1 1052.32   261.9 1035.59
   291.0 1019.77   349.2  995.44   358.9  991.63   387.9  986.80   417.0  974.86
   455.8  968.89   481.5  961.62   496.5  957.49   504.2  956.19   513.9  956.42
   552.6  970.77   581.7  983.72   601.0  994.76   707.5 1029.14   804.2 1064.08
   823.6 1073.29   833.3 1075.09   852.6 1085.83   881.7 1097.99   910.7 1108.48
#Mann= 3 , 0 , 0
       0     0.1       0   481.5   0.045       0   496.5     0.1       0
Bank Sta=   481.5,   496.5
Exp/Cntr=0.3,0.1

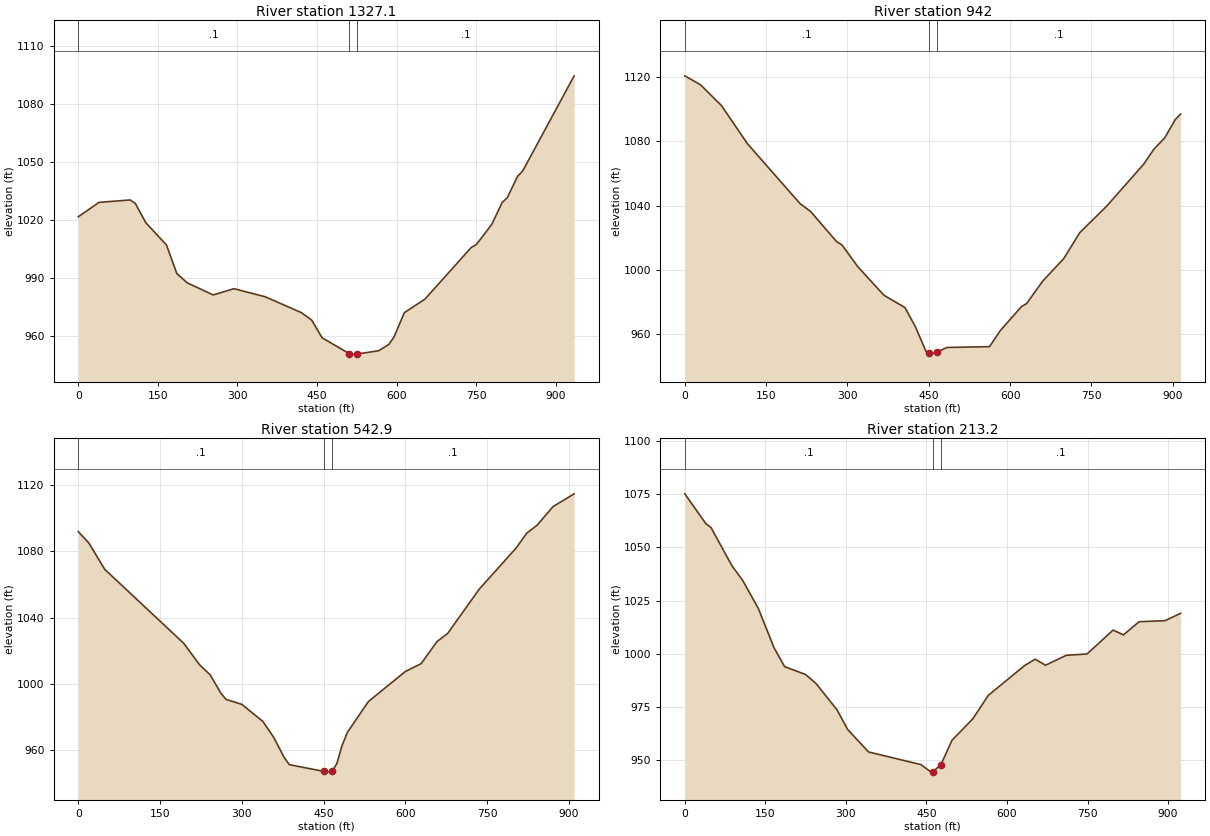
Type RM Length L Ch R = 1 ,1327.1,390.482,385.053,376.441
XS GIS Cut Line= 3
     1763840.241      374088.527     1763390.718      374075.683
     1762911.263      374148.806
#Sta/Elev= 30
       0 1021.67    39.1 1029.09    97.8 1030.35   107.5 1028.52   127.1 1018.59
   166.2 1006.99   185.7  992.20   205.3  987.38   254.2  981.13   293.3  984.36
   351.9  980.21   420.4  971.97   439.9  968.11   459.4  958.94   511.1  950.64
   517.6  950.45   526.1  950.54   566.1  952.20   585.5  955.51   595.2  959.38
   614.6  971.94   653.4  978.96   740.7 1005.72   750.4 1007.25   779.5 1017.72
   798.9 1029.00   808.6 1031.49   828.0 1042.58   837.7 1045.36   934.7 1094.67
#Mann= 3 , 0 , 0
       0     0.1       0   511.1   0.045       0   526.1     0.1       0
Bank Sta=   511.1,   526.1
Exp/Cntr=0.3,0.1

Type RM Length L Ch R = 1 ,942,408.47,399.147,393.007
XS GIS Cut Line= 3
     1763639.034      373557.760     1763215.588      373722.456
     1762820.076      373957.442
#Sta/Elev= 30
       0 1120.83    29.0 1115.26    67.7 1102.29   116.0 1078.37   212.7 1041.25
   232.0 1036.42   280.3 1017.52   290.0 1015.53   319.0 1002.06   367.3  984.24
   406.0  976.59   425.3  964.63   444.7  949.44   450.2  948.39   454.3  947.61
   465.2  948.96   483.7  951.76   562.0  952.26   581.6  962.16   620.7  977.13
   630.5  979.13   659.9  993.00   699.1 1007.17   728.4 1023.24   777.4 1039.49
   845.9 1065.68   865.5 1075.33   885.0 1082.18   904.6 1093.64   914.4 1097.06
#Mann= 3 , 0 , 0
       0     0.1       0   450.2   0.045       0   465.2     0.1       0
Bank Sta=   450.2,   465.2
Exp/Cntr=0.3,0.1

Type RM Length L Ch R = 1 ,542.9,324.78,329.696,334.613
XS GIS Cut Line= 3
     1763256.082      373122.167     1762939.043      373448.528
     1762622.005      373774.890
#Sta/Elev= 30
       0 1091.83    19.4 1084.96    48.4 1069.15   193.6 1024.50   222.7 1011.55
   242.0 1005.56   261.4  994.59   271.1  990.75   300.1  987.76   338.8  977.45
   358.2  968.08   377.6  955.89   387.2  951.43   450.6  947.36   464.7  946.92
   465.6  947.40   474.4  952.02   484.0  962.93   493.7  970.82   532.4  989.46
   600.2 1007.56   629.3 1012.32   658.3 1025.61   677.7 1030.44   735.7 1057.14
   803.5 1081.98   822.9 1090.87   842.2 1095.80   871.3 1106.95   910.0 1114.63
#Mann= 3 , 0 , 0
       0     0.1       0   450.6   0.045       0   465.6     0.1       0
Bank Sta=   450.6,   465.6
Exp/Cntr=0.3,0.1

Type RM Length L Ch R = 1 ,213.2,214.89,213.185,211.481
XS GIS Cut Line= 3
     1763029.641      372896.725     1762772.411      373178.382
     1762319.966      373476.476
#Sta/Elev= 30
       0 1075.17    39.1 1061.20    48.9 1059.29    88.0 1041.29   107.6 1034.59
   136.9 1021.36   166.3 1002.83   185.8  994.02   225.0  990.31   244.5  986.05
   283.6  973.68   303.2  964.52   342.3  953.92   439.5  948.02   458.8  944.46
     462  944.62     477  948.01   497.5  959.41   536.2  969.46   565.3  980.55
   633.0  994.55   652.4  997.49   671.7  994.68   710.4  999.32   749.1  999.96
   797.5 1011.18   816.8 1008.91   845.9 1015.10   894.2 1015.60   923.3 1019.04
#Mann= 3 , 0 , 0
       0     0.1       0     462   0.045       0     477     0.1       0
Bank Sta=     462,     477
Exp/Cntr=0.3,0.1